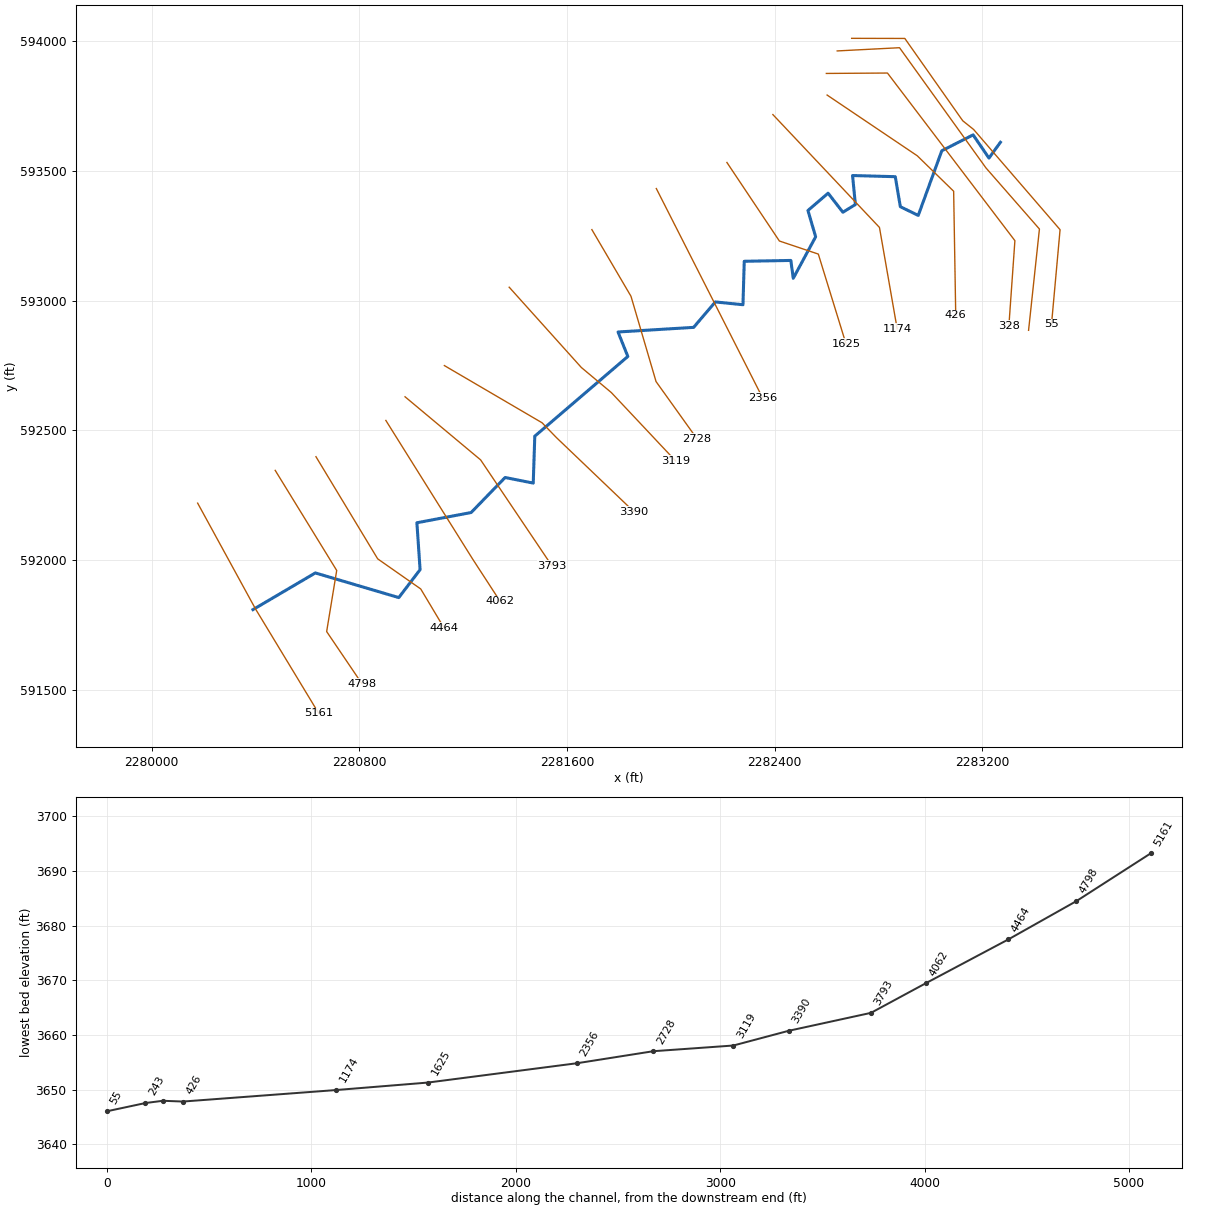
--- REDRN_2T1.prj (project) ---

Proj Title=REDRN_2T1
Current Plan=p01
Default Exp/Contr=0,0
English Units
Geom File=g01
Flow File=f01
Plan File=p01
BEGIN DESCRIPTION:
----------MODEL BY WOOD PLC 2022----------
AFH study
Randolph County, WV
HEC-RAS Version: RAS 6.2
Vertical Datum: NAVD88
Projection: NAD 1983 StatePlane West Virginia S FIPS 4702 (US Feet)
Terrain: 1-meter LIDAR (FEMA Region III 3DEP collected 2016-2018)
Land Use: 2019 NLCD
Hydrologic Method:
WV SIR2010-5033 regression equations
Additional Model Notes:
None
END DESCRIPTION:
DSS Export Rating Curves= 0
DSS Export Rating Curve Sorted= 0
DSS Export Volume Flow Curves= 0
DXF OffsetX= 0
DXF OffsetY= 0
DXF ScaleX= 0
DXF ScaleY= 0

--- REDRN_2T1.p01 (plan) ---

Plan Title=Floodplain
Program Version=6.20
Short Identifier=Floodplain
Geom File=g01
Flow File=f01
Subcritical Flow
K Sum by GR= 0
Std Step Tol= 0.01
Critical Tol= 0.01
Num of Std Step Trials= 20
Max Error Tol= 0.3
Flow Tol Ratio= 0.001
Split Flow NTrial= 30
Split Flow Tol= 0.02
Split Flow Ratio= 0.02
Log Output Level= 0
Friction Slope Method= 1
Unsteady Friction Slope Method= 2
Unsteady Bridges Friction Slope Method= 1
Parabolic Critical Depth
Global Vel Dist= 0 , 0 , 0
Global Log Level= 0
CheckData=True
Encroach Param=-1 ,0,0, 0
Mapping Interval=1HOUR
Computation Time Step Use Courant=        0
Computation Time Step Use Time Series=    0
Computation Time Step Count To Double=0
Computation Time Step Max Doubling=0
Computation Time Step Max Halving=0
Computation Time Step Residence Courant=0
Run HTab= 0
Run UNet= 0
Run Sediment= 0
Run PostProcess= 0
Run WQNet= 0
Run RASMapper=-1
UNET Theta= 0
UNET Theta Warmup= 0
UNET ZTol= 0
UNET ZSATol= 0
UNET MxIter= 0
UNET Max Iter WO Improvement= 0
UNET MaxInSteps= 0
UNET DtIC= 0
UNET DtMin= 0
UNET MaxCRTS= 0
UNET WFStab= 0
UNET SFStab= 0
UNET WFX= 1
UNET SFX= 1
UNET Gravity=32.174
UNET 1D Methodology=Finite Difference
UNET DSS MLevel= 1
UNET Pardiso=0
UNET DZMax Abort= 0
UNET Use Existing IB Tables= 0
UNET Froude Reduction=False
UNET Froude Limit= 0
UNET Froude Power= 0
UNET D1 Cores= 0
UNET WindReference=Eulerian
UNET WindDragFormulation=Hsu (1988)
UNET D2 Coriolis=0
UNET D2 Cores= 0
UNET D2 Theta= 1
UNET D2 Theta Warmup= 1
UNET D2 Z Tol= 0.01
UNET D2 Volume Tol= 0.01
UNET D2 Max Iterations= 20
UNET D2 Equation= 0
UNET D2 RampUpFraction=0.1
UNET D2 TimeSlices= 1
UNET D2 Turbulence Formulation=Non-Conservative (original)
UNET D2 Eddy Viscosity=0.3
UNET D2 Transverse Eddy Viscosity=0.1
UNET D2 Smagorinsky Mixing=0
UNET D2 BCVolumeCheck=0
UNET D2 Cores=0
UNET D2 SolverType=PARDISO (Direct)
UNET D2 Minimum Iterations= 2147483647
UNET D2 Maximum Iterations= 2147483647
UNET D2 Restart Number= 10
UNET D2 Relaxation Coeff=1.3
UNET D2 SOR Precondition Iterations= 10
UNET D2 ILUT Maximum Fill= 8
UNET D2 ILUT Tolerance=1E-08
UNET D1D2 MaxIter= 0
UNET D1D2 ZTol=0.01
UNET D1D2 QTol=0.1
UNET D1D2 MinQTol=1
Write IC File= 0
Write IC File at Fixed DateTime=0
Write IC File at Sim End=0
Echo Input=False
Echo Parameters=False
Echo Output=False
Write Detailed= 0
HDF Write Warmup=0
HDF Write Time Slices=0
HDF Flush=0
HDF Compression= 1
HDF Chunk Size= 1
HDF Spatial Parts= 1
HDF Use Max Rows=0
HDF Fixed Rows= 1
Calibration Method= 0
Calibration Iterations= 20
Calibration Max Change=0.05
Calibration Tolerance=0.2
Calibration Maximum=1.5
Calibration Minimum=0.5
Calibration Optimization Method= 1
WQ AD Non Conservative
WQ ULTIMATE=-1
WQ Max Comp Step=1HOUR
WQ Output Interval=15MIN
WQ Output Selected Increments= 0
WQ Output face flow=0
WQ Output face velocity=0
WQ Output face area=0
WQ Output face dispersion=0
WQ Output cell volume=0
WQ Output cell surface area=0
WQ Output cell continuity=0
WQ Output cumulative cell continuity=0
WQ Output face conc=0
WQ Output face dconc_dx=0
WQ Output face courant=0
WQ Output face peclet=0
WQ Output face adv mass=0
WQ Output face disp mass=0
WQ Output cell mass=0
WQ Output cell source sink temp=0
WQ Output nsm pathways=0
WQ Output nsm derived pathways=0
WQ Create Restart=0
WQ Fixed Restart=0
WQ System Summary=0
WQ Write To DSS=0
Sorting and Armoring Iterations= 10
XS Update Threshold= 0.02
Bed Roughness Predictor= 0
Hydraulics Update Threshold= 0.02
Energy Slope Method= 1
Volume Change Method= 1
Sediment Retention Method= 0
Sediment TS Multiplier= 1
Warm Up Method= 0
XS Weighting Method= 0
Number of US Weighted Cross Sections= 1
Number of DS Weighted Cross Sections= 1
Upstream XS Weight=0
Main XS Weight=1
Downstream XS Weight=0
Number of DS XS's Weighted with US Boundary= 1
Upstream Boundary Weight= 1
Weight of XSs Associated with US Boundary= 0
Number of US XS's Weighted with DS Boundary= 1
Downstream Boundary Weight= 0.5
Weight of XSs Associated with DS Boundary= 0.5
Percentile Method= 0
Sediment Output Level= 3
Mass or Volume Output= 0
Output Increment Type= 1
Profile and TS Output Increment= 1
Transport Output Increment 1
XS Output Flag= 0
XS Output Increment= 10
Read HDF5 Sediment Hotstart= 0
Sediment Hotstart Type= 0
Write Gradation File= 0
Read Gradation Hotstart= 0
Write HDF5 File= 1
Write Binary Output= 1
Write DSS Sediment File= 0
DSS Sediment Output Type= 1
SV Curve= 0
Specific Gage Flag= 0
Subcell Erosion Methods= 0
Subcell Deposition Methods= 0
Advection Scheme= 1
Matrix Solver= 0
Implicit Weighting Factor= 1
Maximum Outer Loop Convergence Iterations= 5
Convergence Maximum Absolute= 0.001
Convergence RMSE= 0.0001
Grain Fractions Max Abs Error= 0.001
Max Subgrid Regions= 1
Max Subgrid Length Scale= 3.402823E+38
Initial Layer Thickness= 3.402823E+38
Min Layer Thickness= 3.402823E+38
Max Layer Thickness= 3.402823E+38
Number of Layers= 5

--- REDRN_2T1.f01 (steady flow) ---

Flow Title=Flow
Program Version=6.20
Number of Profiles= 1
Profile Names=P100yr
River Rch & RM=REDRN_2T1,Main            ,5161
     352
River Rch & RM=REDRN_2T1,Main            ,3390
     397
Boundary for River Rch & Prof#=REDRN_2T1,Main            , 1
Up Type= 0
Dn Type= 3
Dn Slope=0.004432
DSS Import GetInterval= 0
DSS Import GetPeak= 0
DSS Import FillOption= 0

--- REDRN_2T1.g01 (geometry) ---

Geom Title=Geometry
Program Version=6.20

River Reach=REDRN_2T1       ,Main
Reach XY= 30
     2280390.359      591809.471     2280630.611       591950.84
     2280952.077      591855.826     2281034.109      591963.377
     2281021.869      592144.107     2281230.807       592183.53
     2281361.764       592318.51     2281470.046      592296.971
     2281476.036      592477.701     2281834.441      592784.645
     2281796.681      592879.046     2282087.922      592896.841
     2282171.516      592994.758     2282278.027      592984.081
     2282282.938      593151.424     2282462.402      593154.654
     2282471.777      593085.904     2282557.974      593245.799
     2282528.287      593347.102     2282605.891      593413.768
     2282662.922      593340.331       2282711.1      593370.018
     2282700.162      593481.737     2282864.745       593477.31
     2282884.277      593361.685     2282953.244      593328.091
     2283043.957      593577.225     2283164.615      593638.421
     2283225.596      593549.011      2283269.78      593609.885

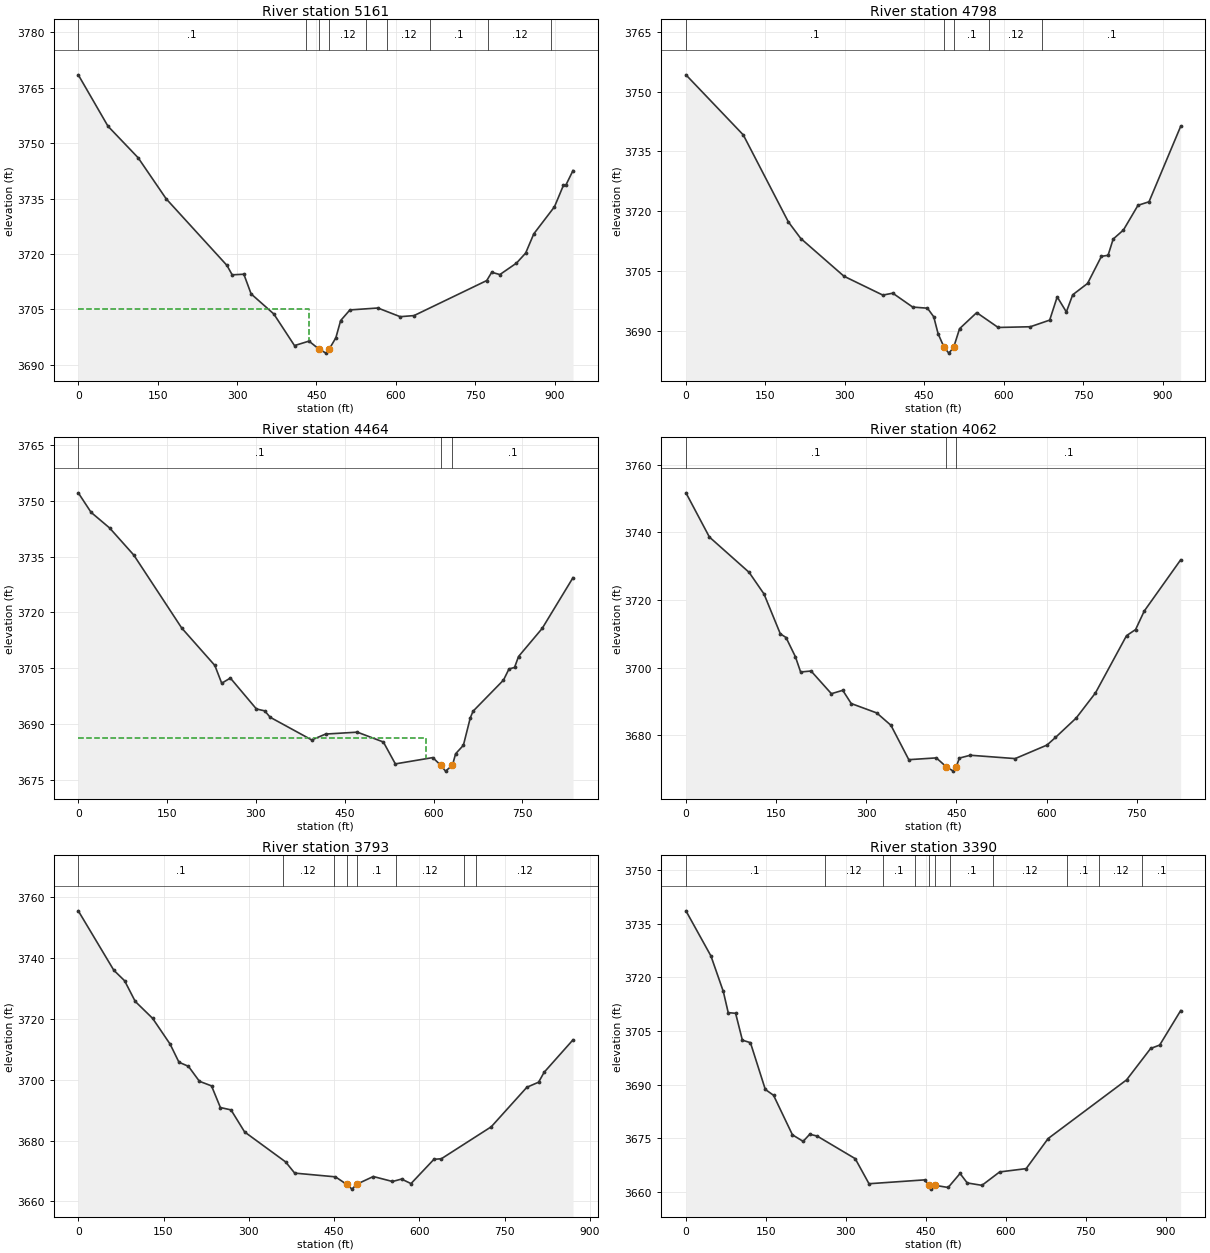
Type RM Length L Ch R = 1 ,5161    ,368.5,363.3,356
XS GIS Cut Line= 3
     2280177.262      592219.724     2280399.846      591812.634
2280643.74118276591409.802482884
#Sta/Elev= 30
       0 3768.49    56.1 3754.59   113.1 3746.05   166.1 3734.94     281 3716.91
   290.8 3714.37   312.9 3714.53   326.6 3709.21   369.5 3703.78   408.6 3695.22
     436 3696.43   454.2 3694.34     468 3693.18  474.373694.323   486.7 3697.31
   495.8 3701.99   513.3 3704.87   566.2 3705.39   608.3 3703.04   634.5 3703.34
   771.9 3712.82   781.3 3715.06   796.7 3714.44   828.1 3717.54   845.4 3720.25
   860.8 3725.46   899.9 3732.79   916.9 3738.62   921.6 3738.71   934.9 3742.59
#Mann= 9 ,-1,0
       0      .1       0     430     .12       0   454.2    .045       0
  474.37     .12       0  543.97      .1       0  583.97     .12       0
  663.97      .1       0  773.97     .12       0  893.97      .1       0
#XS Ineff= 2 , 0
          436.82 3705.17
Permanent Ineff=
       F       F
Bank Sta=454.2,474.37
XS Rating Curve= 0 ,0
Exp/Cntr=0.3,0.1

Type RM Length L Ch R = 1 ,4798    ,322.4,333.5,344.6
XS GIS Cut Line= 4
2280475.98001694592345.9971237642280712.93857988591960.358678183
2280674.21986045591724.9488640142280810.50975286591523.611522948
#Sta/Elev= 30
       0 3754.19   108.3 3739.13   193.4 3717.34   216.9 3713.18   298.4 3703.73
   371.8    3699   390.6 3699.48   428.2    3696   456.1 3695.72     468 3693.55
   476.1 3689.36   487.4 3685.93   496.4 3684.46   505.53685.875   516.7 3690.58
   549.1 3694.61   589.6 3690.89   650.4 3691.07   686.9 3692.73   701.1 3698.55
   718.4 3694.78   730.4 3699.08   758.5 3701.93   784.6 3708.71   797.2 3708.97
   806.8 3713.04   826.2 3715.31   853.7  3721.5   874.5 3722.38   934.3 3741.29
#Mann= 5 ,-1,0
       0      .1       0   487.4    .045       0   505.5      .1       0
  572.62     .12       0  672.62      .1       0
Bank Sta=487.4,505.5
XS Rating Curve= 0 ,0
Exp/Cntr(USF)=0,0
Exp/Cntr=0.3,0.1

Type RM Length L Ch R = 1 ,4464    ,402.2,402.4,396.7
XS GIS Cut Line= 4
2280633.01374878592398.6077487772280870.81922188592005.067646082
2281036.62707437591889.1162344222281125.62270169591740.401267712
#Sta/Elev= 30
       0 3752.08    21.6 3746.85    52.9 3742.66    93.7  3735.4   174.6 3715.84
   230.6 3705.79   242.2 3701.02   256.8 3702.41   300.8 3694.12   314.8 3693.61
   324.1 3691.89   394.2 3685.81   417.6 3687.39   471.2  3687.9   515.2 3685.26
   535.4 3679.39   598.6 3681.08   611.9 3679.05   620.2 3677.45  631.783679.027
   637.2 3682.11   650.3 3684.39     662 3691.77   666.7 3693.53     718 3701.86
   727.3 3704.85   736.7 3705.25   743.4 3708.18   783.3 3715.71   835.4 3729.33
#Mann= 3 ,-1,0
       0      .1       0   611.9    .045       0  631.78      .1       0
#XS Ineff= 2 , 0
             587 3686.29
Permanent Ineff=
       F       F
Bank Sta=611.9,631.78
XS Rating Curve= 0 ,0
Exp/Cntr=0.3,0.1

Type RM Length L Ch R = 1 ,4062    ,266.2,269.1,266.9
XS GIS Cut Line= 3
2280902.27364108592538.2758818342281237.40434585  592003.0517871
2281341.89933425591842.318620831
#Sta/Elev= 30
       0 3751.64      39 3738.59   105.1 3728.16   129.9 3721.77     157 3710.02
   166.5 3708.92   182.1 3703.26   190.8 3698.74   208.2 3699.03     242 3692.33
   260.9 3693.33     275 3689.43   317.5 3686.65   341.1    3683   370.8 3672.85
   416.6 3673.38   433.2 3670.75   444.9 3669.47  449.863670.762   454.9 3673.32
   473.2 3674.16   547.8 3673.17   600.7 3677.16   614.8  3679.4   649.3 3685.14
   681.4 3692.56   733.1 3709.47   748.2 3711.27   762.5 3716.71   823.2 3731.86
#Mann= 3 ,-1,0
       0      .1       0   433.2    .045       0  449.86      .1       0
Bank Sta=433.2,449.86
XS Rating Curve= 0 ,0
Exp/Cntr=0.3,0.1

Type RM Length L Ch R = 1 ,3793    ,398.7,402.8,402.4
XS GIS Cut Line= 3
2280976.22587205592629.4181500342281267.39064221592386.264591977
2281541.51917581591978.943663513
#Sta/Elev= 30
       0 3755.58    62.5 3736.04    81.5 3732.58   100.2 3725.78   130.8 3720.21
   161.5 3711.75   177.1 3705.79   193.8 3704.43   213.1 3699.51   234.4    3698
     250 3690.88   268.7  3690.1   292.6 3682.85   364.7    3673   380.7 3669.31
   452.4 3668.08   472.3 3665.59   481.6 3664.04  489.733665.635     519 3668.19
   552.7 3666.55   568.7 3667.35   585.3 3665.86   625.7 3673.85   638.7 3674.03
   726.5 3684.55   789.1 3697.54   809.8 3699.22   819.4 3702.45   870.3 3713.15
#Mann= 8 ,-1,0
       0      .1       0     360     .12       0  449.34      .1       0
   472.3    .045       0  489.73      .1       0  559.34     .12       0
  679.34      .1       0  699.34     .12       0
Bank Sta=472.3,489.73
XS Rating Curve= 0 ,0
Exp/Cntr(USF)=0,0
Exp/Cntr=0.3,0.1

Type RM Length L Ch R = 1 ,3390    ,269.8,270.6,270.6
XS GIS Cut Line= 4
2281127.71845354592749.636433981  2281504.065782592529.294704265
2281559.43810072592472.1595428182281857.69590934592187.030824906
#Sta/Elev= 30
       0 3738.65    46.9 3726.01    70.1 3716.08    79.3 3710.16    93.2 3709.97
   105.9 3702.45     121 3701.75   148.9 3688.66   164.4 3687.02   199.8 3675.96
   219.9 3674.13   232.3 3676.12   246.2 3675.61   317.6 3669.29   343.5 3662.27
   447.8 3663.35  455.87 3661.86   459.3 3660.76  466.41 3661.85     492 3661.22
   514.3 3665.14   527.8 3662.49   555.4 3661.82   588.6 3665.57   638.4  3666.5
   679.6 3674.92   826.8 3691.34   871.9 3700.12   888.9 3701.08   928.3 3710.73
#Mann= 11 ,-1,0
       0      .1       0     260     .12       0     370      .1       0
     430     .05       0  455.87    .045       0  466.41     .05       0
  496.11      .1       0  575.67     .12       0  715.67      .1       0
  775.67     .12       0  855.67      .1       0
Bank Sta=455.87,466.41
XS Rating Curve= 0 ,0
Exp/Cntr=0.3,0.1

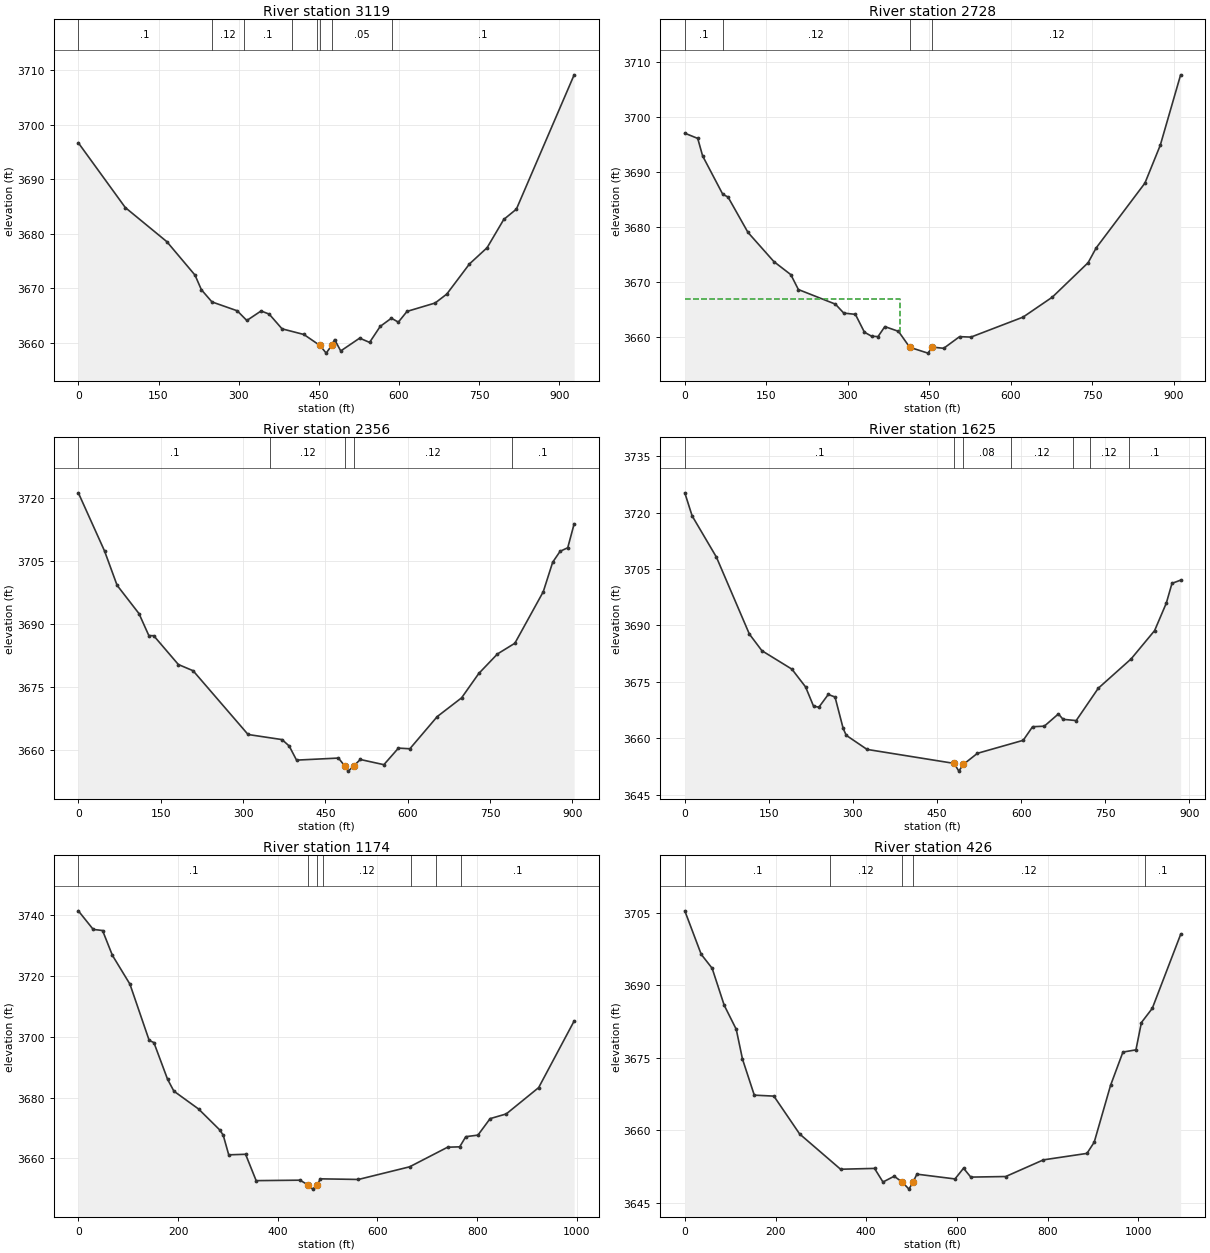
Type RM Length L Ch R = 1 ,3119    ,388.9,391.6,349.4
XS GIS Cut Line= 4
2281377.47716268593051.5299386112281655.26573367592742.377976377
2281771.02792249592645.5759431332282018.35216268592382.530938611
#Sta/Elev= 30
       0 3696.68    87.8  3684.8   165.6 3678.53   218.3 3672.39   230.2 3669.71
     250 3667.47   297.3 3665.84   315.2 3664.06   341.9 3665.81   357.1 3665.23
   381.1 3662.53     422 3661.49     4523659.472   463.7 3658.07   474.73659.583
   479.4 3660.56   490.9 3658.47   526.3 3660.82   544.9 3660.04   564.8 3662.98
   585.7 3664.48   598.7 3663.76   614.9 3665.73   667.5 3667.27   689.3 3668.91
   731.7 3674.44   764.7 3677.42   795.9 3682.61   819.5  3684.5   927.6 3709.16
#Mann= 8 ,-1,0
       0      .1       0     250     .12       0     310      .1       0
     400     .12       0  445.62     .05       0     452    .045       0
   474.7     .05       0  586.52      .1       0
Bank Sta=452,474.7
XS Rating Curve= 0 ,0
Exp/Cntr=0.3,0.1

Type RM Length L Ch R = 1 ,2728    ,365,372,361
XS GIS Cut Line= 4
2281695.91658558593273.4280489032281846.62268496593016.605344392
2281943.14475367 592688.098171162282101.44953179592466.800985329
#Sta/Elev= 30
       0 3697.08    23.8 3696.13    32.8 3692.94    69.9 3685.95    79.5 3685.46
   116.2 3679.02     164 3673.69   195.1 3671.32     209 3668.61   277.1 3665.95
   292.5 3664.32   313.9 3664.09   330.5 3660.84   343.7 3660.11   355.5 3660.04
   368.1 3661.86   393.1    3661   413.9 3658.09   447.3 3657.03   455.6 3658.12
   476.4 3657.91   505.6 3660.03   526.5 3659.95   622.4 3663.59   676.3 3667.23
   742.1  3673.5   756.9 3676.19   846.6 3687.99   874.9  3694.9   912.3 3707.71
#Mann= 4 ,-1,0
       0      .1       0      70     .12       0   413.9    .045       0
   455.6     .12       0
#XS Ineff= 2 , 0
          396.39 3666.97
Permanent Ineff=
       F       F
Bank Sta=413.9,455.6
XS Rating Curve= 0 ,0
Exp/Cntr=0.3,0.1

Type RM Length L Ch R = 1 ,2356    ,715.7,731.1,730.2
XS GIS Cut Line= 2
2281944.19385794593431.6700167432282353.06353518592626.320652479
#Sta/Elev= 30
       0 3721.32    47.7 3707.44    70.6 3699.23   110.5 3692.47   128.4 3687.23
   137.4 3687.18   182.2 3680.31   209.1 3678.82   309.2 3663.59   371.1 3662.37
   384.1 3660.84   397.5 3657.47   473.8 3657.96  485.333656.079   491.8 3654.84
  501.353656.035   513.6 3657.62   556.6 3656.38   583.1 3660.34   603.9 3660.18
   653.8 3667.87   698.1 3672.34   729.5 3678.17   763.5 3682.83   795.2 3685.39
   846.9 3697.69   864.1 3704.75   877.6 3707.35   891.5  3708.2   903.2 3713.92
#Mann= 5 ,-1,0
       0      .1       0     350     .12       0  485.33    .045       0
  501.35     .12       0     790      .1       0
Bank Sta=485.33,501.35
XS Rating Curve= 0 ,0
Exp/Cntr(USF)=0,0
Exp/Cntr=0.3,0.1

Type RM Length L Ch R = 1 ,1625    ,447.8,450.3,441.4
XS GIS Cut Line= 4
2282216.16813471593532.0651581872282418.25549984593229.554776284
2282568.26882542593179.1678550862282675.10266192592832.820962141
#Sta/Elev= 30
       0 3725.24    13.1 3719.11    56.4 3708.16   115.2 3687.71   137.6 3683.29
   191.1 3678.39   215.5 3673.66   229.6 3668.58   239.2 3668.28   255.9 3671.67
     268 3670.99   282.5 3662.65     288 3660.81   325.1 3657.07   480.6 3653.35
   488.8  3651.3     4973653.098     522 3656.03   603.7 3659.49   620.4  3663.1
   641.3 3663.24   666.5  3666.5   674.8 3665.06   698.2 3664.73   737.6 3673.32
   796.2 3681.12   838.1 3688.64     859 3695.95   869.1 3701.19   884.5 3702.04
#Mann= 7 ,-1,0
       0      .1       0   480.6    .045       0     497     .08       0
  582.05     .12       0  692.05      .1       0  722.05     .12       0
  792.05      .1       0
Bank Sta=480.6,497
XS Rating Curve= 0 ,0
Exp/Cntr=0.3,0.1

Type RM Length L Ch R = 1 ,1174    ,734.8,748.1,741.3
XS GIS Cut Line= 3
2282393.26362141593716.5204634642282803.80965011593281.795554854
2282872.05482638592891.055075718
#Sta/Elev= 30
       0 3741.37    29.9 3735.26    48.6  3734.9    68.3 3726.76   103.5 3717.28
   142.1 3698.81   151.6 3698.07     179 3686.03   191.7 3682.12   241.2 3676.26
   283.9 3669.34   290.7 3667.62   301.7  3661.2   335.5 3661.38   356.7 3652.72
   444.7 3652.87   461.2 3651.27   470.3 3649.93  478.983651.306   485.5 3653.31
   561.9 3653.11   664.5 3657.26   740.7  3663.7     765 3663.83   777.2 3667.16
   801.6 3667.68     826 3673.09   858.4 3674.64   923.4 3683.29   994.6 3705.18
#Mann= 7 ,-1,0
       0      .1       0   461.2    .045       0  478.98      .1       0
     490     .12       0  667.94     .08       0  717.94     .12       0
  767.94      .1       0
Bank Sta=461.2,478.98
XS Rating Curve= 0 ,0
Exp/Cntr=0.3,0.1

Type RM Length L Ch R = 1 ,426     ,99.5,97.9,94.9
XS GIS Cut Line= 4
 2282602.1437243 593791.772165892282949.45431328593557.850895161
2283089.62850986 593421.248015692283097.66397336592942.691522902
#Sta/Elev= 30
       0 3705.46    36.2 3696.45    60.3 3693.56    86.9  3685.9   113.4 3680.93
   127.2 3674.75   153.2 3667.29   196.4 3667.09   253.2 3659.25   343.4 3651.95
   418.3 3652.12   436.9  3649.3   461.6  3650.5  479.29 3649.29   494.2 3647.83
   503.2  3649.3   511.7 3650.93   595.7 3649.94   614.5 3652.16   630.5 3650.32
   707.5 3650.44   790.6 3653.89   886.6 3655.23   902.6 3657.55   938.6 3669.31
   965.9 3676.21   994.6 3676.67  1006.6 3682.32  1030.6 3685.26  1093.1 3700.57
#Mann= 5 ,-1,0
       0      .1       0     320     .12       0  479.29    .045       0
   503.2     .12       0 1014.47      .1       0
Bank Sta=479.29,503.2
XS Rating Curve= 0 ,0
Exp/Cntr(USF)=0,0
Exp/Cntr=0.3,0.1

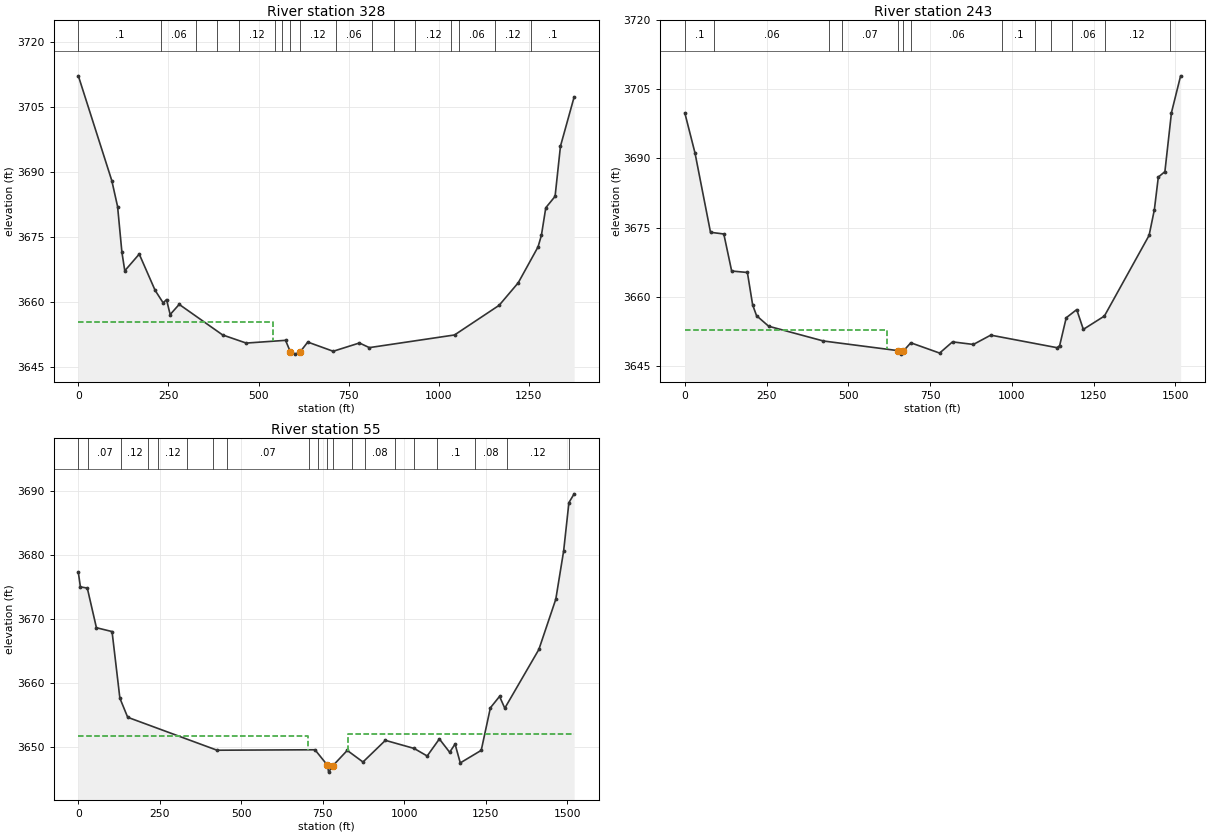
Type RM Length L Ch R = 1 ,328     ,85.8,85.5,85.2
XS GIS Cut Line= 4
2282599.22836389593875.0483062332282834.63817806593876.597055011
2283325.59154051593230.7688148222283302.36030885592902.434074007
#Sta/Elev= 30
       0 3712.15    92.9 3687.97   108.9 3682.01   120.9 3671.48   128.9 3667.19
     169 3671.04     213 3662.69   235.4 3659.79   244.7 3660.55   254.8  3657.1
   279.9 3659.44   400.5 3652.39   465.8 3650.52     575 3651.15   588.3 3648.51
   601.5 3647.97   615.8 3648.52   636.6 3650.75   707.2 3648.63   779.9 3650.54
   807.5 3649.47  1043.9 3652.39  1167.7 3659.23  1220.7 3664.43  1275.6  3672.7
  1284.9 3675.36  1297.1 3681.73  1322.9 3684.36  1337.8 3695.92  1375.8 3707.29
#Mann= 17 ,-1,0
       0      .1       0     230     .06       0  325.41      .1       0
  385.41     .08       0  445.41     .12       0  545.41     .07       0
  565.41     .12       0   588.3    .045       0   615.8     .12       0
  715.41     .06       0  815.41     .12       0  875.41     .06       0
  935.41     .12       0 1035.41     .07       0 1056.67     .06       0
 1156.67     .12       0 1256.67      .1       0
#XS Ineff= 2 , 0
          540.79 3655.31
Permanent Ineff=
       F       F
Bank Sta=588.3,615.8
XS Rating Curve= 0 ,0
Exp/Cntr(USF)=0,0
Exp/Cntr=0.3,0.1

Type RM Length L Ch R = 1 ,243     ,185.3,187.7,187
XS GIS Cut Line= 5
2282641.04458088593961.7782377692282881.10064138593974.168227989
2283214.08162853593511.0923435372283420.06521593593275.682529368
2283378.24899894592885.397837456
#Sta/Elev= 30
       0  3699.9    31.2 3691.19    78.6 3673.99   119.3 3673.62   143.3 3665.59
   191.4 3665.27   207.4 3658.26   219.4  3655.9   256.4 3653.61   423.8 3650.41
  651.373648.323   661.7 3647.56   668.33648.223     691 3650.02   779.2 3647.79
   818.6 3650.22   882.4 3649.66   935.5 3651.68  1138.1 3648.96  1146.2  3649.4
  1166.3 3655.45  1198.4 3657.22  1218.6 3652.93    1283 3655.82  1419.7 3673.32
  1435.8 3678.89  1447.9 3685.97    1468 3687.14  1488.1 3699.96  1516.1 3707.93
#Mann= 13 ,-1,0
       0      .1       0      90     .06       0  440.38     .08       0
  480.38     .07       0  651.37    .045       0   668.3     .07       0
  690.38     .06       0  970.74      .1       0 1070.74     .07       0
 1120.74      .1       0 1183.55     .06       0 1283.55     .12       0
 1483.55      .1       0
#XS Ineff= 2 , 0
          618.05 3652.79
Permanent Ineff=
       F       F
Bank Sta=651.37,668.3
XS Rating Curve= 0 ,0
Exp/Cntr(USF)=0,0
Exp/Cntr=0.3,0.1

Type RM Length L Ch R = 1 ,55      ,,,
XS GIS Cut Line= 6
2282696.71278233594010.2840037452282901.50981612594009.854605267
2283124.65489103593692.686368116 2283166.6930527 593659.05583878
2283499.59348907593273.0968977732283466.60743944592909.147032312
#Sta/Elev= 30
       0 3677.22     6.4 3674.97    27.5 3674.79    55.5  3668.6   103.5    3668
   127.5  3657.6   151.5 3654.62   425.7 3649.48   726.3 3649.55   764.23647.155
   768.2 3646.06  781.013647.053   825.3 3649.45   873.6 3647.64   942.4 3651.02
  1030.4 3649.76  1070.6 3648.58    1108 3651.24  1139.6 3649.16  1156.2 3650.44
  1172.2  3647.5  1236.5 3649.46  1264.6  3656.1  1292.7 3657.88  1308.8 3656.04
  1413.4 3665.21  1465.4 3673.06  1489.5 3680.61  1505.6 3688.13  1521.7  3689.5
#Mann= 20 ,-1,0
       0      .1       0      30     .07       0     130     .12       0
   214.8     .06       0   244.8     .12       0   334.8     .06       0
   414.8     .08       0   454.8     .07       0  706.43     .06       0
  736.43     .07       0   764.2    .045       0  781.01     .07       0
   840.4     .06       0   880.4     .08       0   970.4      .1       0
  1030.4     .08       0  1100.4      .1       0 1216.22     .08       0
 1316.22     .12       0 1506.22      .1       0
#XS Ineff= 2 , 0
          705.85 3651.64  827.15         3651.98
Permanent Ineff=
       F       F
Bank Sta=764.2,781.01
XS Rating Curve= 0 ,0
Exp/Cntr(USF)=0,0
Exp/Cntr=0.3,0.1
LCMann Table=0

Chan Stop Cuts=-1
Use User Specified Reach Order=0
Composite Channel Slope=5